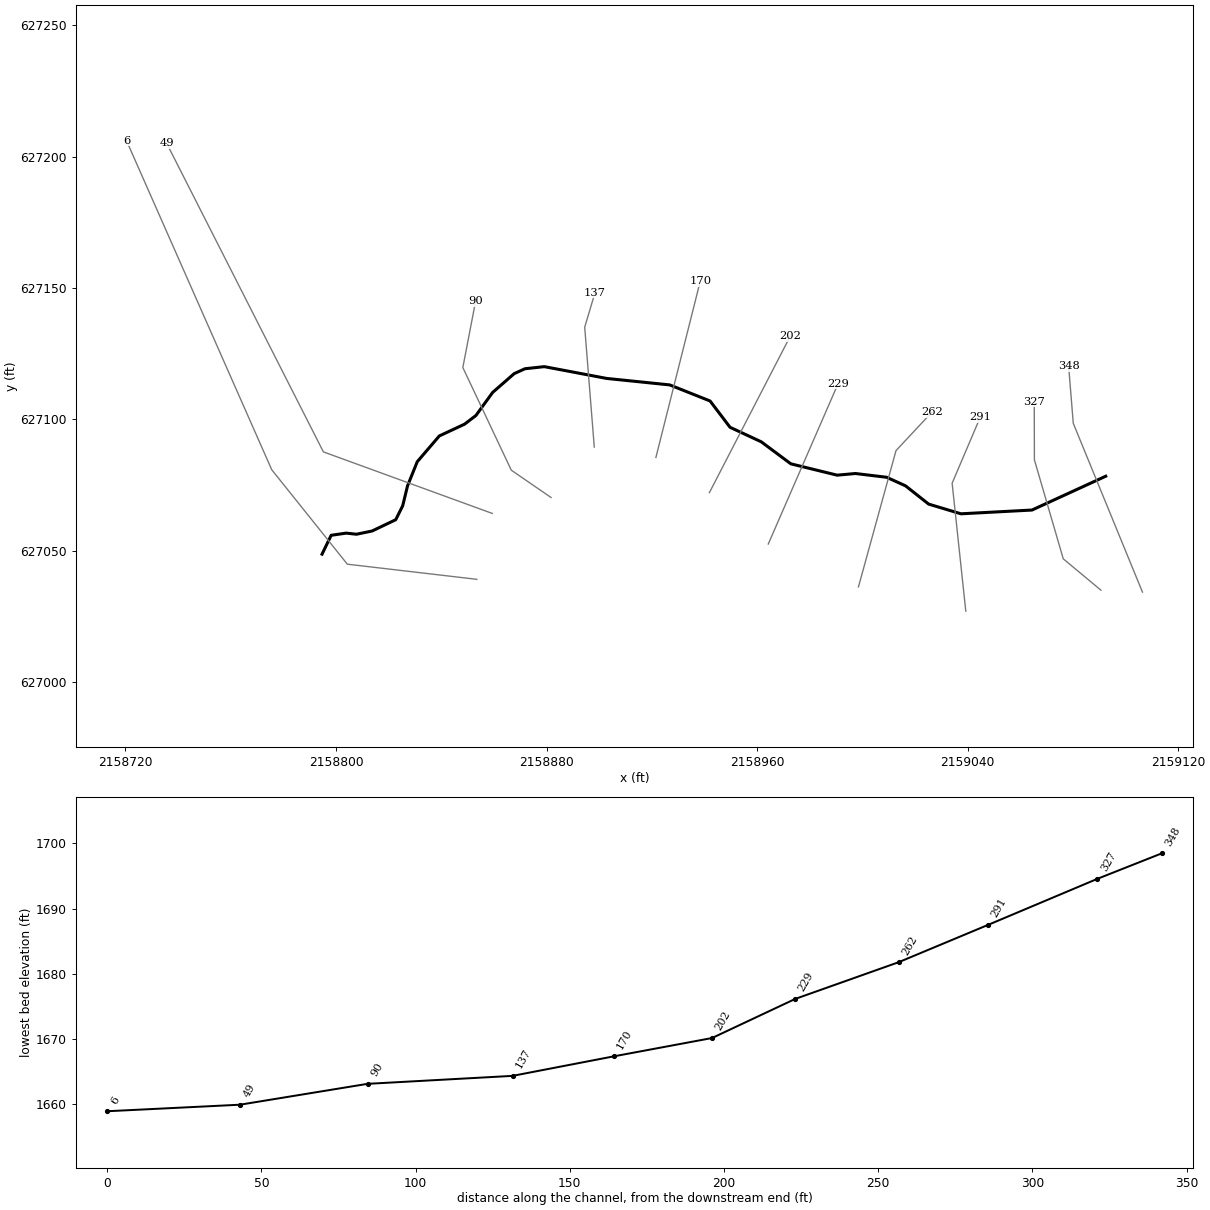
--- TURKEYFK.prj (project) ---

Proj Title=TURKEYFK
Current Plan=p01
Default Exp/Contr=0,0
English Units
Geom File=g01
Flow File=f01
Plan File=p01
BEGIN DESCRIPTION:
---------- MODELED AS PART OF WVEMD CTP PROGRAM, 2023----------
Stream Name: Turkey Fork
Flood Zone:  AFH
Upshur County, WV
HEC-RAS Version: RAS 6.3
Vertical Datum: NAVD88
Projection: NAD 1983 StatePlane West Virginia S FIPS 4702 (US Feet)
Terrain: 1-meter LIDAR (FEMA Region III 3DEP collected 2016-2018)
Land Use: 2019 NLCD
Hydrologic Method:
WV SIR2010-5033 regression equations
Additional Model Notes:
None
END DESCRIPTION:
DSS Export Rating Curves= 0
DSS Export Rating Curve Sorted= 0
DSS Export Volume Flow Curves= 0
DXF OffsetX= 0
DXF OffsetY= 0
DXF ScaleX= 0
DXF ScaleY= 0

--- TURKEYFK.p01 (plan) ---

Plan Title=Floodplain
Program Version=6.30
Short Identifier=Floodplain
Geom File=g01
Flow File=f01
Subcritical Flow
K Sum by GR= 0
Std Step Tol= 0.01
Critical Tol= 0.01
Num of Std Step Trials= 20
Max Error Tol= 0.3
Flow Tol Ratio= 0.001
Split Flow NTrial= 30
Split Flow Tol= 0.02
Split Flow Ratio= 0.02
Log Output Level= 0
Friction Slope Method= 1
Unsteady Friction Slope Method= 2
Unsteady Bridges Friction Slope Method= 1
Parabolic Critical Depth
Global Vel Dist= 0 , 0 , 0
Global Log Level= 0
CheckData=False
Encroach Param=-1 ,0,0, 0
Mapping Interval=1HOUR
Computation Time Step Use Courant=        0
Computation Time Step Use Time Series=    0
Computation Time Step Count To Double=0
Computation Time Step Max Doubling=0
Computation Time Step Max Halving=0
Computation Time Step Residence Courant=0
Run HTab= 0
Run UNet= 0
Run Sediment= 0
Run PostProcess= 0
Run WQNet= 0
Run RASMapper=-1
UNET Theta= 0
UNET Theta Warmup= 0
UNET ZTol= 0
UNET ZSATol= 0
UNET MxIter= 0
UNET Max Iter WO Improvement= 0
UNET MaxInSteps= 0
UNET DtIC= 0
UNET DtMin= 0
UNET MaxCRTS= 0
UNET WFStab= 0
UNET SFStab= 0
UNET WFX= 1
UNET SFX= 1
UNET Gravity=32.17405
UNET 1D Methodology=Finite Difference
UNET DSS MLevel= 1
UNET Pardiso=0
UNET DZMax Abort= 0
UNET Use Existing IB Tables= 0
UNET Froude Reduction=False
UNET Froude Limit= 0
UNET Froude Power= 0
UNET D1 Cores= 0
UNET WindReference=Eulerian
UNET WindDragFormulation=Hsu (1988)
UNET D2 Coriolis=0
UNET D2 Cores= 0
UNET D2 Theta= 1
UNET D2 Theta Warmup= 1
UNET D2 Z Tol= 0.01
UNET D2 Volume Tol= 0.01
UNET D2 Max Iterations= 20
UNET D2 Equation= 0
UNET D2 RampUpFraction=0.1
UNET D2 TimeSlices= 1
UNET D2 Turbulence Formulation=Non-Conservative (original)
UNET D2 Eddy Viscosity=0.3
UNET D2 Transverse Eddy Viscosity=0.1
UNET D2 Smagorinsky Mixing=0
UNET D2 BCVolumeCheck=0
UNET D2 Cores=0
UNET D2 SolverType=PARDISO (Direct)
UNET D2 Minimum Iterations= 3
UNET D2 Maximum Iterations= 30
UNET D2 Restart Number= 10
UNET D2 Relaxation Coeff=1.3
UNET D2 SOR Precondition Iterations= 10
UNET D2 ILUT Maximum Fill= 8
UNET D2 ILUT Tolerance=1E-08
UNET D2 Convergence Tolerance=0.00001
UNET D1D2 MaxIter= 0
UNET D1D2 ZTol=0.01
UNET D1D2 QTol=0.1
UNET D1D2 MinQTol=1
Write IC File= 0
Write IC File at Fixed DateTime=0
Write IC File at Sim End=0
Echo Input=False
Echo Parameters=False
Echo Output=False
Write Detailed= 0
HDF Write Warmup=0
HDF Write Time Slices=0
HDF Flush=0
HDF Compression= 1
HDF Chunk Size= 1
HDF Spatial Parts= 1
HDF Use Max Rows=0
HDF Fixed Rows= 1
Calibration Method= 0
Calibration Iterations= 20
Calibration Max Change=0.05
Calibration Tolerance=0.2
Calibration Maximum=1.5
Calibration Minimum=0.5
Calibration Optimization Method= 1
WQ AD Non Conservative
WQ ULTIMATE=-1
WQ Max Comp Step=1HOUR
WQ Output Interval=15MIN
WQ Output Selected Increments= 0
WQ Output face flow=0
WQ Output face velocity=0
WQ Output face area=0
WQ Output face dispersion=0
WQ Output cell volume=0
WQ Output cell surface area=0
WQ Output cell continuity=0
WQ Output cumulative cell continuity=0
WQ Output face conc=0
WQ Output face dconc_dx=0
WQ Output face courant=0
WQ Output face peclet=0
WQ Output face adv mass=0
WQ Output face disp mass=0
WQ Output cell mass=0
WQ Output cell source sink temp=0
WQ Output nsm pathways=0
WQ Output nsm derived pathways=0
WQ Create Restart=0
WQ Fixed Restart=0
WQ System Summary=0
WQ Write To DSS=0
Sorting and Armoring Iterations= 10
XS Update Threshold= 0.02
Bed Roughness Predictor= 0
Hydraulics Update Threshold= 0.02
Energy Slope Method= 1
Volume Change Method= 1
Sediment Retention Method= 0
Sediment TS Multiplier= 1
Warm Up Method= 0
XS Weighting Method= 0
Number of US Weighted Cross Sections= 1
Number of DS Weighted Cross Sections= 1
Upstream XS Weight=0
Main XS Weight=1
Downstream XS Weight=0
Number of DS XS's Weighted with US Boundary= 1
Upstream Boundary Weight= 1
Weight of XSs Associated with US Boundary= 0
Number of US XS's Weighted with DS Boundary= 1
Downstream Boundary Weight= 0.5
Weight of XSs Associated with DS Boundary= 0.5
Percentile Method= 0
Sediment Output Level= 3
Mass or Volume Output= 0
Output Increment Type= 1
Profile and TS Output Increment= 1
Transport Output Increment 1
XS Output Flag= 0
XS Output Increment= 10
Read HDF5 Sediment Hotstart= 0
Sediment Hotstart Type= 0
Write Gradation File= 0
Read Gradation Hotstart= 0
Write HDF5 File= 1
Write Binary Output= 1
Write DSS Sediment File= 0
DSS Sediment Output Type= 1
SV Curve= 0
Specific Gage Flag= 0
Subcell Erosion Methods= 0
Subcell Deposition Methods= 0
Advection Scheme= 1
Matrix Solver= 0
Implicit Weighting Factor= 1
Maximum Outer Loop Convergence Iterations= 5
Convergence Maximum Absolute= 0.001
Convergence RMSE= 0.0001
Grain Fractions Max Abs Error= 0.001
Max Subgrid Regions= 1
Max Subgrid Length Scale= 3.402823E+38
Initial Layer Thickness= 3.402823E+38
Min Layer Thickness= 3.402823E+38
Max Layer Thickness= 3.402823E+38
Number of Layers= 5

--- TURKEYFK.f01 (steady flow) ---

Flow Title=Flows
Program Version=6.30
Number of Profiles= 1
Profile Names=01pct
River Rch & RM=TURKEYFK,Main,348
     553
Boundary for River Rch & Prof#=TURKEYFK,Main            , 1
Up Type= 0
Dn Type= 3
Dn Slope=0.01463
DSS Import GetInterval= 0
DSS Import GetPeak= 0
DSS Import FillOption= 0

--- TURKEYFK.g01 (geometry) ---

Geom Title=Geometry
Program Version=6.31

River Reach=TURKEYFK        ,Main
Reach XY= 30
     2159092.466      627078.313      2159064.45      627065.435
     2159037.465      627064.004     2159025.189      627067.696
     2159016.404       627074.65     2159009.221      627077.912
     2158997.374      627079.343      2158990.42      627078.713
     2158972.821      627083.034     2158961.575      627091.419
     2158949.727      627096.942     2158942.144      627106.958
     2158926.806      627113.081     2158902.882      627115.542
     2158879.159      627120.035     2158871.805      627119.234
     2158867.713      627117.374     2158859.529       627110.22
     2158853.176      627101.435     2158848.883      627098.144
     2158839.268      627093.651     2158830.884      627083.836
     2158827.192       627074.65     2158825.361      627067.066
     2158822.699      627061.744     2158813.714      627057.451
      2158807.79      627056.221     2158803.898       627056.65
     2158798.175       627055.82     2158794.712      627048.637

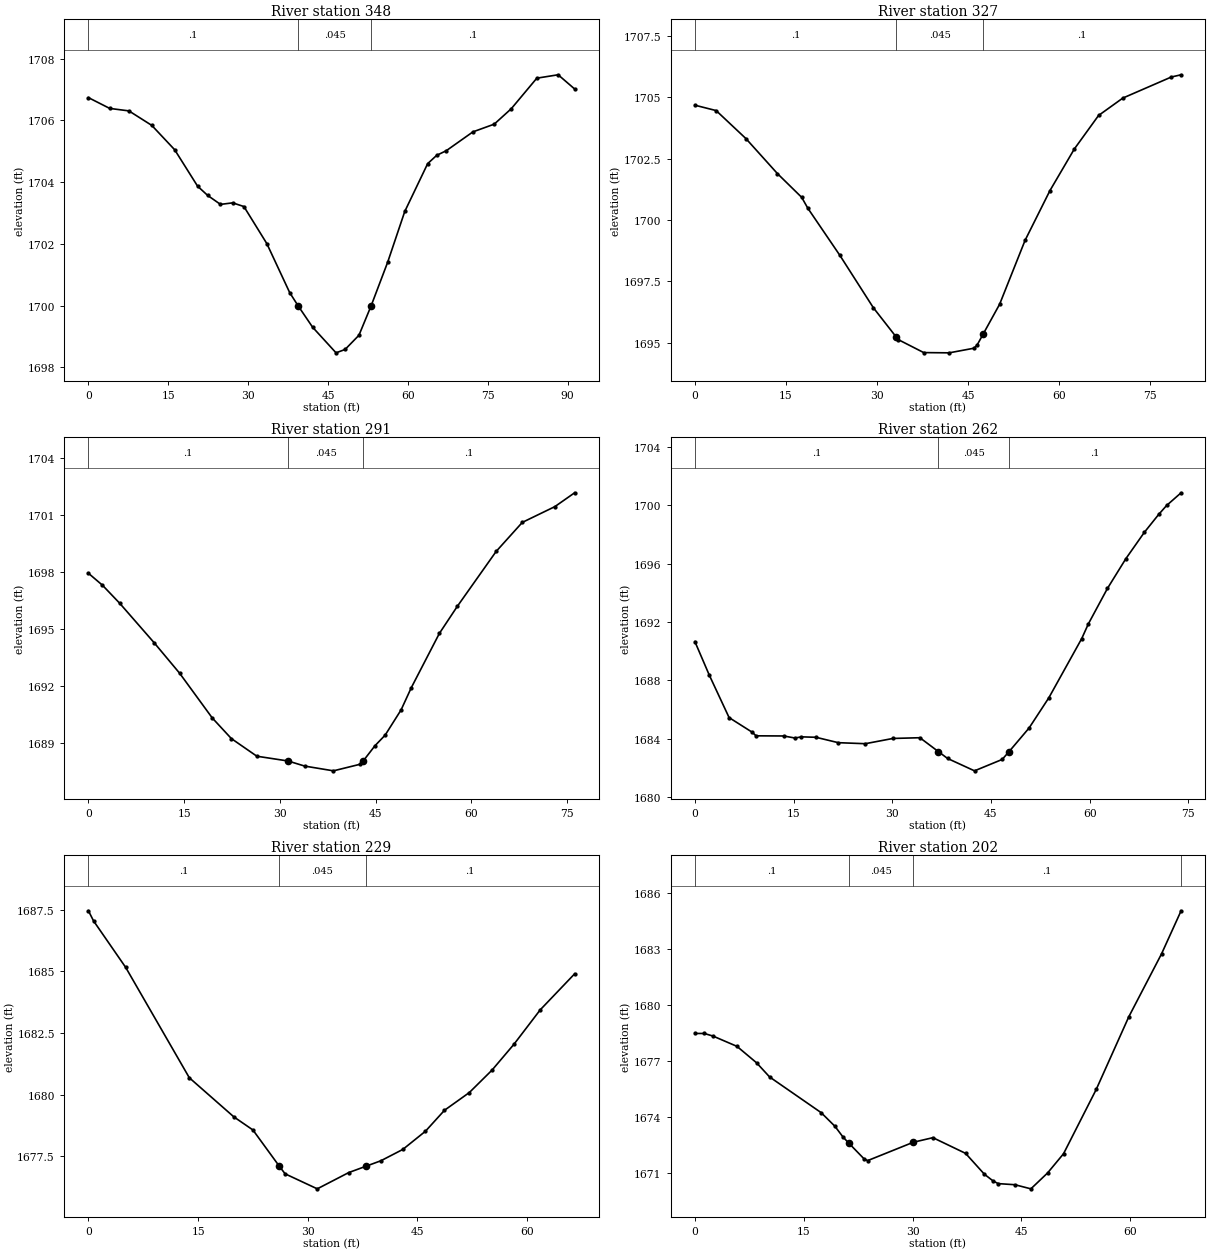
Type RM Length L Ch R = 1 ,348     ,20.8,20.8,20.8
XS GIS Cut Line= 3
2159106.42176676627034.1863171022159080.13404915627098.455608167
2159078.37033372627120.276008552
#Sta/Elev= 29
       0 1706.74       4 1706.39     7.6 1706.31    11.9 1705.84    16.2 1705.05
    20.5 1703.87    22.4 1703.57    24.8 1703.28    27.1 1703.33    29.2 1703.21
    33.5 1702.01    37.8 1700.42   39.35    1700    42.1  1699.3    46.5 1698.47
    48.2 1698.58    50.8 1699.04    53.1    1700    56.2 1701.41    59.4 1703.05
    63.7  1704.6    65.4 1704.87    67.2 1705.02    72.2 1705.63    76.2 1705.88
    79.4 1706.38    84.2 1707.37    88.2 1707.48    91.3 1707.02
#Mann= 3 ,-1,0
       0      .1       0   39.35    .045       0    53.1      .1       0
Bank Sta=39.35,53.1
XS Rating Curve= 0 ,0
Exp/Cntr=0.3,0.1

Type RM Length L Ch R = 1 ,327     ,37.6,35.5,32.8
XS GIS Cut Line= 4
2159090.64169519627034.9227979772159076.33616792 627046.85157002
2159065.36885534627084.5517070152159065.30693026627106.750019791
#Sta/Elev= 23
       0 1704.68     3.5 1704.46     8.4 1703.32    13.6 1701.89    17.6 1700.92
    18.6 1700.48    23.9 1698.55    29.4 1696.42    33.21695.215    33.5 1695.12
    37.7 1694.59    41.9 1694.58      46 1694.77    46.5  1694.9    47.51695.349
    50.2 1696.56    54.4 1699.17    58.5  1701.2    62.5 1702.89    66.5 1704.26
    70.5 1704.97    78.5 1705.83    80.1 1705.92
#Mann= 3 ,-1,0
       0      .1       0    33.2    .045       0    47.5      .1       0
Bank Sta=33.2,47.5
XS Rating Curve= 0 ,0
Exp/Cntr=0.3,0.1

Type RM Length L Ch R = 1 ,291     ,33.3,29,24.7
XS GIS Cut Line= 3
2159039.29731294627026.9513315792159034.10938786627075.660183675
2159044.77345607627100.735154872
#Sta/Elev= 23
       0 1697.92     2.2 1697.29     4.9 1696.34    10.3 1694.26    14.3 1692.65
    19.4  1690.3    22.4 1689.21    26.4 1688.28    31.31688.028    33.9 1687.76
    38.4 1687.51    42.5 1687.85   43.04 1688.02    44.9 1688.83    46.5 1689.39
      49 1690.72    50.6 1691.89      55 1694.75    57.8 1696.17    63.9 1699.07
      68  1700.6    73.1 1701.43    76.2 1702.16
#Mann= 3 ,-1,0
       0      .1       0    31.3    .045       0   43.04      .1       0
Bank Sta=31.3,43.04
XS Rating Curve= 0 ,0
Exp/Cntr(USF)=0,0
Exp/Cntr=0.3,0.1

Type RM Length L Ch R = 1 ,262     ,34.9,33.5,31.8
XS GIS Cut Line= 3
2158998.51445749 627036.174309492159012.78125144627088.053560244
2159026.47160928 627102.75268129
#Sta/Elev= 28
       0 1690.65     2.2 1688.34     5.2 1685.44     8.7 1684.44     9.3 1684.19
    13.5 1684.18    15.2 1684.04    16.2 1684.12    18.4 1684.09    21.8 1683.72
    25.9 1683.65    30.1 1684.01    34.2 1684.06      371683.112    38.4 1682.64
    42.5 1681.79    46.7 1682.57    47.7 1683.08    50.8 1684.73    53.8  1686.8
    58.8 1690.86    59.8 1691.86    62.7 1694.29    65.5 1696.33    68.3 1698.13
    70.5 1699.37    71.7 1699.98    73.9 1700.85
#Mann= 3 ,-1,0
       0      .1       0      37    .045       0    47.7      .1       0
Bank Sta=37,47.7
XS Rating Curve= 0 ,0
Exp/Cntr(USF)=0,0
Exp/Cntr=0.3,0.1

Type RM Length L Ch R = 1 ,229     ,27.7,27,26.1
XS GIS Cut Line= 2
2158964.25296594627052.4964272042158990.73696945627113.459605096
#Sta/Elev= 20
       0 1687.46      .7 1687.05     5.1 1685.16    13.8 1680.68    19.9 1679.09
    22.5 1678.56   26.13 1677.08    26.9 1676.78    31.3 1676.17    35.6 1676.83
    37.91677.081      40 1677.31      43 1677.77    46.1 1678.51    48.7 1679.36
    52.1 1680.08    55.2 1680.99    58.2 1682.04    61.8 1683.44    66.5  1684.9
#Mann= 3 ,-1,0
       0      .1       0   26.13    .045       0    37.9      .1       0
Bank Sta=26.13,37.9
XS Rating Curve= 0 ,0
Exp/Cntr(USF)=0,0
Exp/Cntr=0.3,0.1

Type RM Length L Ch R = 1 ,202     ,29.5,31.9,33.8
XS GIS Cut Line= 2
2158941.87960875627072.0574579282158972.57483211627131.574487264
#Sta/Elev= 26
       0 1678.49     1.3 1678.49     2.5 1678.35     5.8  1677.8     8.5 1676.92
    10.3 1676.16    17.4 1674.25    19.3 1673.52    20.4 1672.95    21.21672.622
    23.3 1671.78    23.8 1671.68    30.11672.665    32.8 1672.91    37.3 1672.07
    39.9 1670.95    41.1 1670.59    41.8 1670.45    44.1 1670.39    46.3 1670.17
    48.6 1671.02    50.8 1672.05    55.3 1675.49    59.8 1679.39    64.3 1682.75
      67 1685.06
#Mann= 4 ,-1,0
       0      .1       0    21.2    .045       0    30.1      .1       0
   66.97     .08       0
Bank Sta=21.2,30.1
XS Rating Curve= 0 ,0
Exp/Cntr(USF)=0,0
Exp/Cntr=0.3,0.1

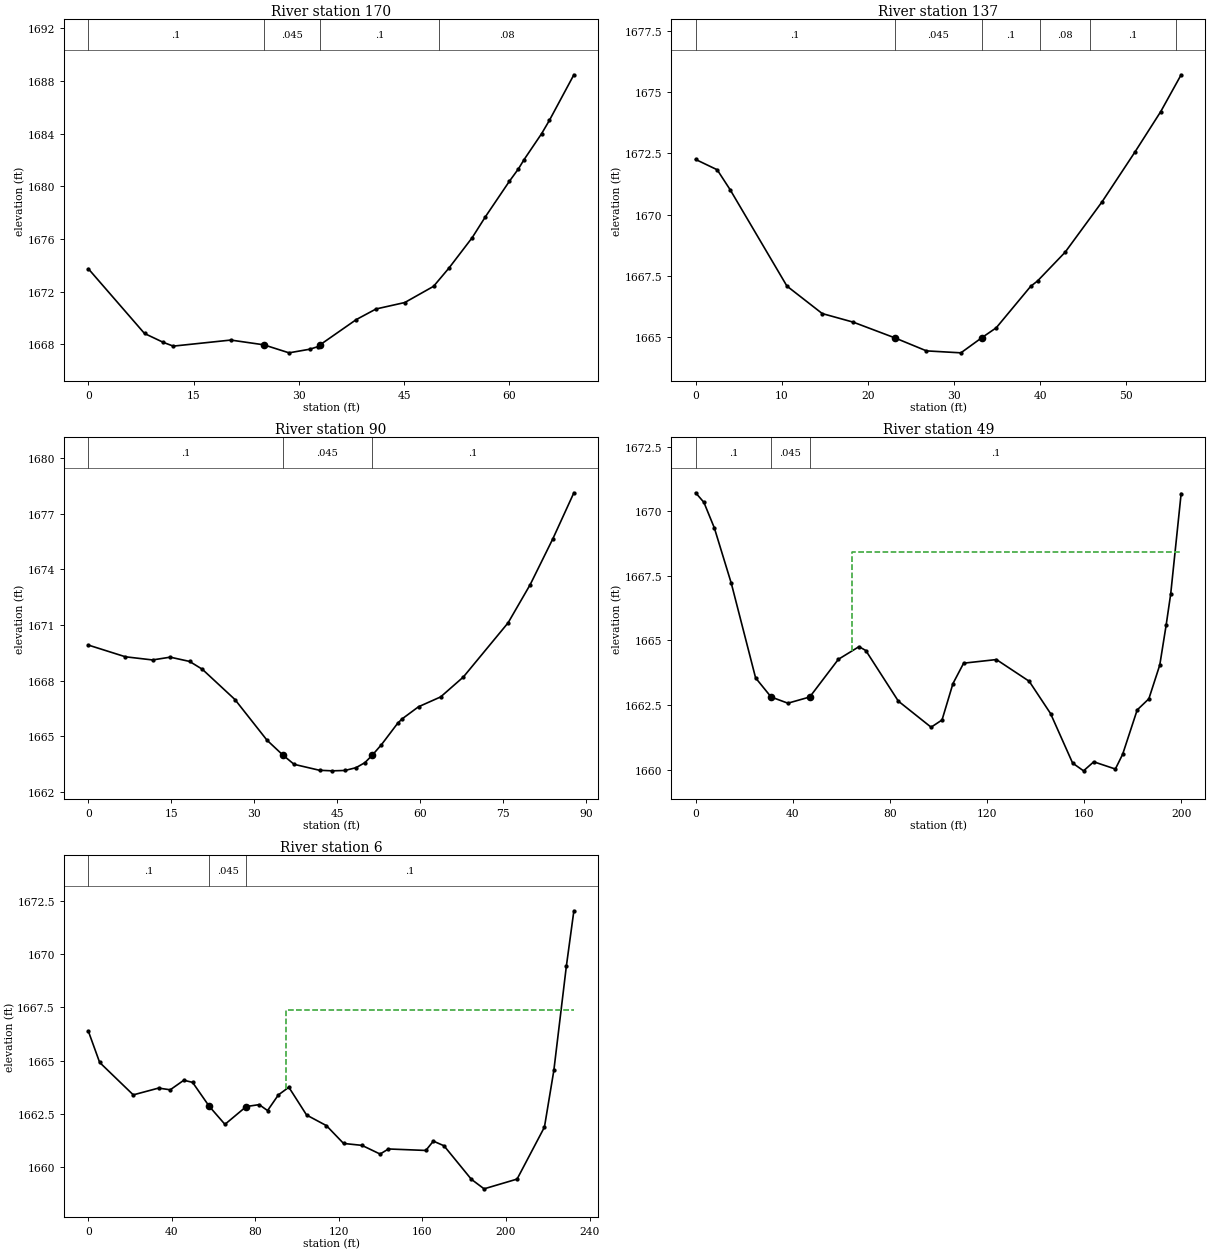
Type RM Length L Ch R = 1 ,170     ,29.5,32.8,36.5
XS GIS Cut Line= 2
2158921.56023554627085.4595977062158938.42099203627152.614405625
#Sta/Elev= 23
       0 1673.74       8 1668.83    10.7 1668.15    12.1 1667.87    20.3 1668.33
      25 1667.97    28.6 1667.36    31.6 1667.64    32.7 1667.83      33 1667.96
    38.2 1669.89      41 1670.69    45.1 1671.18    49.2 1672.41    51.4  1673.8
    54.7  1676.1    56.6  1677.7      60 1680.38    61.3 1681.33    62.1 1682.03
    64.6    1684    65.7    1685    69.2 1688.47
#Mann= 4 ,-1,0
       0      .1       0      25    .045       0      33      .1       0
      50     .08       0
Bank Sta=25,33
XS Rating Curve= 0 ,0
Exp/Cntr(USF)=0,0
Exp/Cntr=0.3,0.1

Type RM Length L Ch R = 1 ,137     ,43.4,47,50.3
XS GIS Cut Line= 3
2158898.14525428627089.4210731572158894.50531631627135.049784729
 2158898.4379689627148.262418816
#Sta/Elev= 18
       0 1672.25     2.5 1671.83       4 1671.02    10.6 1667.09    14.7 1665.97
    18.3 1665.6223.138541664.979    26.8 1664.45    30.8 1664.37    33.2 1664.98
    34.9 1665.39    38.9 1667.08    39.7  1667.3    42.9 1668.47    47.2 1670.53
      51 1672.55      54  1674.256.36915  1675.7
#Mann= 6 ,-1,0
       0      .1       023.13854    .045       0    33.2      .1       0
      40     .08       0   45.77      .1       0   55.77     .08       0
Bank Sta=23.13854,33.2
XS Rating Curve= 0 ,0
Exp/Cntr(USF)=0,0
Exp/Cntr=0.3,0.1

Type RM Length L Ch R = 1 ,90      ,33.4,41.4,53.5
XS GIS Cut Line= 4
2158881.72602057627070.2089663372158866.62014461627080.607685451
2158848.20376821627119.6935169732158853.06083451627144.963813981
#Sta/Elev= 26
       0 1669.92     6.7 1669.29    11.6 1669.12    14.8 1669.27    18.3 1669.04
    20.6 1668.62    26.5 1666.99    32.3  1664.835.138561664.009    37.2  1663.5
    41.8 1663.18    44.1 1663.15    46.4 1663.17    48.4 1663.32      50 1663.59
51.318291663.987      53 1664.56    55.9  1665.7    56.7 1665.94    59.7  1666.6
    63.7 1667.13    67.8  1668.2    75.9 1671.12    79.9 1673.18      84 1675.65
87.79301 1678.12
#Mann= 3 ,-1,0
       0      .1       035.13856    .045       051.31829      .1       0
Bank Sta=35.13856,51.31829
XS Rating Curve= 0 ,0
Exp/Cntr(USF)=0,0
Exp/Cntr=0.3,0.1

Type RM Length L Ch R = 1 ,49      ,43,43,43
XS GIS Cut Line= 3
2158859.37319931627064.149921035  2158795.218715627087.582338347
2158735.67996323627205.053289594
#Sta/Elev= 30
       0 1670.72     3.4 1670.35     7.7 1669.36    14.7 1667.21    24.7 1663.55
   31.09 1662.81      38 1662.57      47 1662.81    58.8 1664.27    67.3 1664.76
    70.1 1664.61    83.5 1662.65      97 1661.64   101.5 1661.92     106 1663.33
   110.4 1664.12   123.9 1664.26   137.4 1663.42   146.2 1662.17   155.3 1660.25
   159.8 1659.95     164  1660.3   172.9 1660.02   175.9 1660.59   181.9 1662.31
   186.7 1662.74   191.2 1664.05   193.8 1665.58   195.7  1666.8     200 1670.69
#Mann= 3 ,-1,0
       0      .1       0   31.09    .045       0      47      .1       0
#XS Ineff= 2 , 0
                           64.41         1668.42
Permanent Ineff=
       F       F
Bank Sta=31.09,47
XS Rating Curve= 0 ,0
Exp/Cntr(USF)=0,0
Exp/Cntr=0.3,0.1

Type RM Length L Ch R = 1 ,6       ,,,
XS GIS Cut Line= 4
2158853.52080724627039.0535180182158804.31633195627044.821926593
 2158775.5947202627080.7814632912158720.40211555627206.104544088
#Sta/Elev= 30
       0 1666.38     5.4 1664.91    21.5 1663.38    33.6  1663.7    39.2 1663.62
    45.7 1664.07    49.9 1663.97   57.88 1662.84    65.4 1661.99    75.6 1662.83
    81.8 1662.92    85.8 1662.64      91 1663.38      96 1663.74   104.5 1662.43
     114 1661.93   122.2 1661.09     131    1661   139.7 1660.59   143.7 1660.83
   161.6 1660.76   165.2  1661.2   170.3 1660.98   183.4  1659.4   189.5 1658.95
   205.3 1659.41   218.4 1661.86   222.9 1664.53   228.9 1669.45   232.5 1672.06
#Mann= 3 ,-1,0
       0      .1       0   57.88    .045       0    75.6      .1       0
#XS Ineff= 2 , 0
                           94.54          1667.4
Permanent Ineff=
       F       F
Bank Sta=57.88,75.6
XS Rating Curve= 0 ,0
Exp/Cntr(USF)=0,0
Exp/Cntr=0.3,0.1
LCMann Table=0

Chan Stop Cuts=-1
Use User Specified Reach Order=0
Composite Channel Slope=5